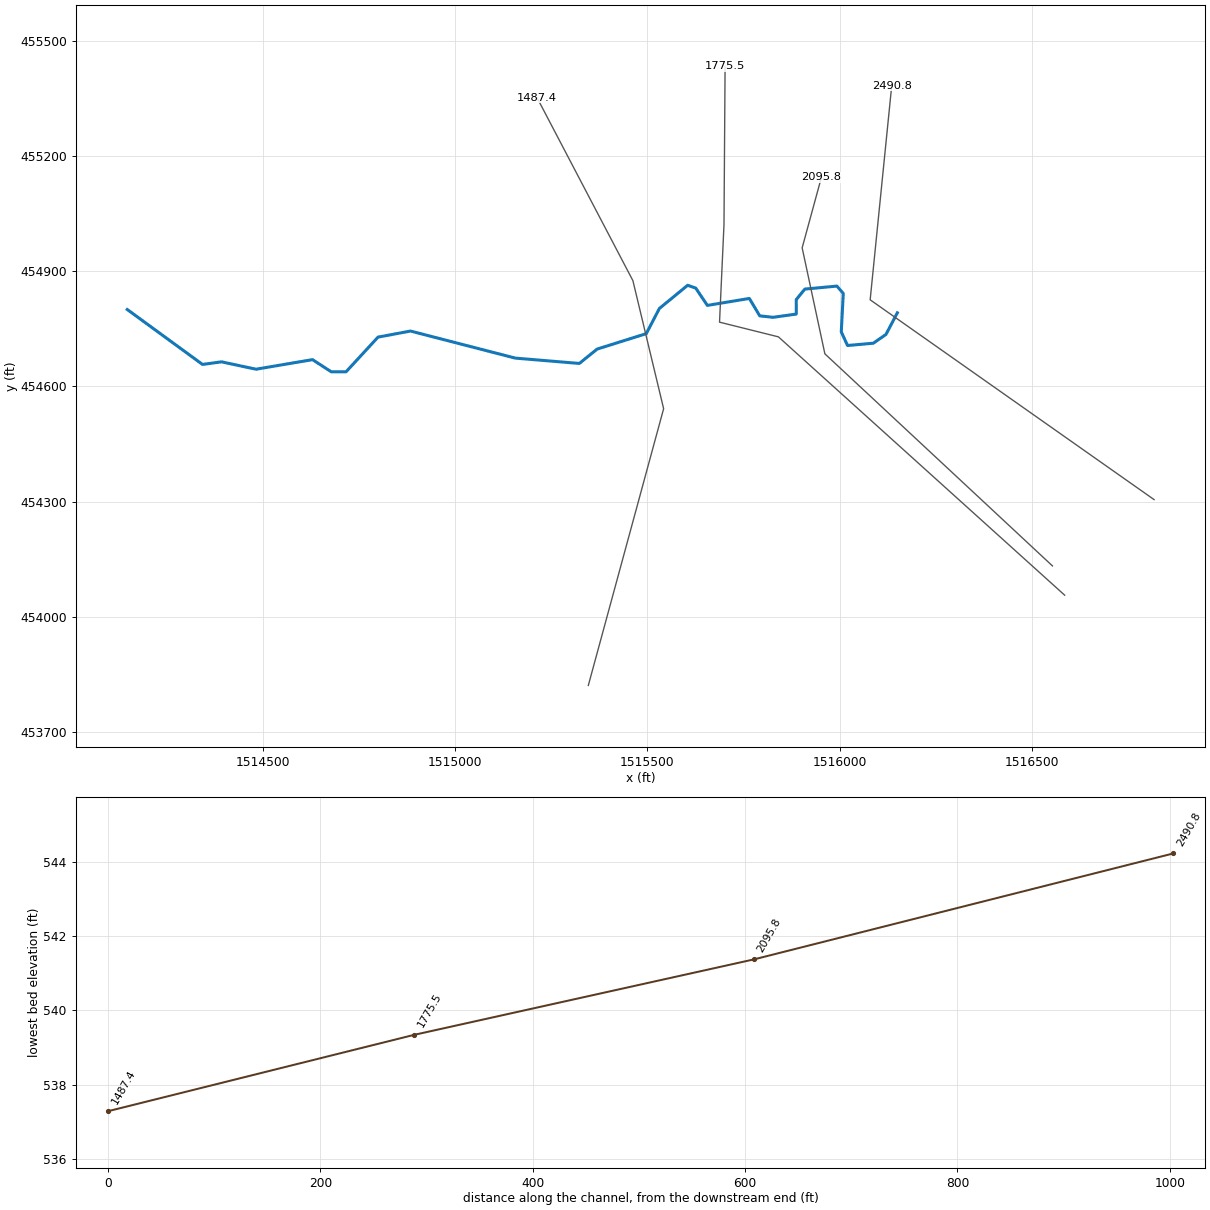
--- ELIJAHCR.prj (project) ---

Proj Title=ELIJAHCR
Current Plan=p01
Default Exp/Contr=0,0
English Units
Geom File=g01
Flow File=f01
Plan File=p01
BEGIN DESCRIPTION:
END DESCRIPTION:
DSS Export Rating Curves= 0
DSS Export Rating Curve Sorted= 0
DSS Export Volume Flow Curves= 0
DXF OffsetX= 0
DXF OffsetY= 0
DXF ScaleX= 0
DXF ScaleY= 0

--- ELIJAHCR.p01 (plan) ---

Plan Title=Floodplain
Program Version=4.00
Geom File=g01
Flow File=f01
K Sum by GR=0
Std Step Tol=0.01
Critical Tol=0.01
Num of Std Step Trials=20
Max Error Tol=0.3
Flow Tol Ratio=0.001
Split Flow NTrial=30
Split Flow Tol=0.02
Split Flow Ratio=0.02
Log Output Level=0
Friction Slope Method=1
Unsteady Friction Slope Method=2
Unsteady Bridges Friction Slope Method=1
Global Log Level=0
CheckData=False
Run HTab=0
Run UNet=0
Run PostProcess=0
UNET Theta=0
UNET Theta Warmup=0
UNET ZTol=0
UNET ZSATol=0
UNET MxIter=0
UNET MaxInSteps=0
UNET DtIC=0
UNET DtMin=0
UNET MaxCRTS=0
UNET WFStab=0
UNET SFStab=0
UNET WFX=0
UNET SFX=0
UNET DSS MLevel=0
UNET DZMax Abort=0
UNET Convert EG Bridges=0
UNET Use Existing IB Tables=0
UNET Froude Limit=0
UNET Froude Power=0
Write IC File=0
Echo Input=False
Echo Output=False
Write Detailed=0

--- ELIJAHCR.f01 (steady flow) ---

Flow Title=NFF Regression Equation
Program Version=4.00
Number of Profiles=1
Profile Names=P100yr
River Rch & RM=ELIJAHCR,Main      ,2490.8
     445
River Rch & RM=ELIJAHCR,Main      ,1775.5
     447
River Rch & RM=ELIJAHCR,Main      ,1487.4
     559
Boundary for River Rch & Prof#=ELIJAHCR,Main      ,1
Up Type=0
Dn Type=3
Dn Slope=0.006926

--- ELIJAHCR.g01 (geometry) ---

Geom Title=USGS 10m DEM
Program Version=4.00

River Reach=ELIJAHCR        ,Main
Reach XY= 30
     1516149.501      454791.667      1516119.88      454735.282
     1516087.086      454712.578     1516020.098      454706.574
     1516003.799      454742.018     1516009.016      454842.119
      1515992.39      454861.206     1515909.145      454853.402
     1515886.819      454826.125     1515886.899      454788.392
     1515826.467      454779.956     1515791.862       454783.78
     1515764.943      454829.052     1515655.856      454810.943
     1515625.659      454855.965     1515604.693      454863.344
     1515531.145      454802.869     1515497.142      454737.449
     1515369.428      454697.251     1515323.238      454659.879
     1515156.861      454673.763     1514884.498       454744.22
     1514800.103       454728.38     1514717.138      454638.213
     1514678.661      454638.137     1514629.891      454669.801
     1514483.126      454644.891     1514393.453      454664.065
     1514344.076      454657.337     1514148.554      454800.244

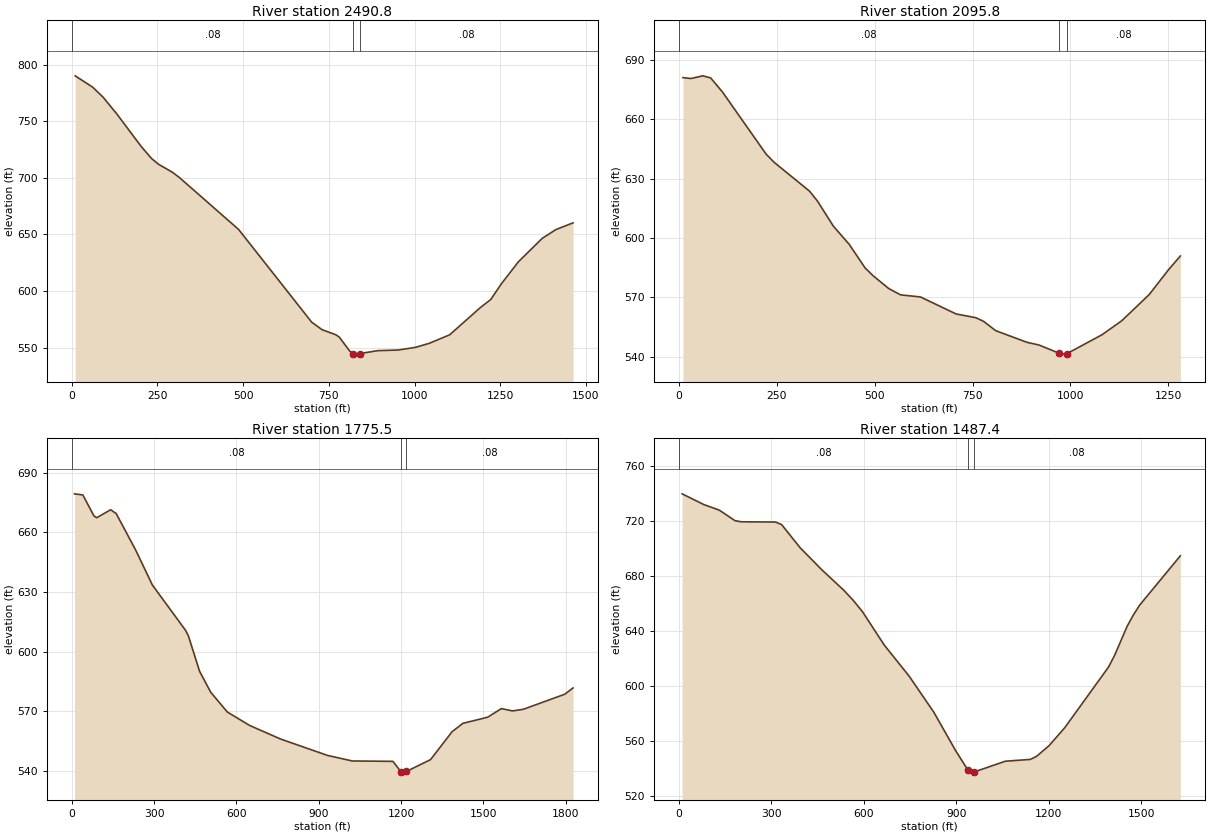
Type RM Length L Ch R = 1 ,2490.8  ,413.9,394.9,374.4
XS GIS Cut Line= 3
     1516816.583      454305.555     1516078.888      454825.516
     1516134.868      455382.474
#Sta/Elev= 30
    10.1  790.22    60.8  780.27    91.3  771.42   131.8  756.44   202.8  727.71
   233.2  717.04   253.5     712   294.1  704.92   314.4  700.23   486.8  654.43
   699.7  572.56   730.1  565.85   770.7  561.33   780.8  559.13   811.3  546.75
   821.5   544.4   831.5  544.24   841.5  544.79   892.4   547.3   952.5  547.87
  1002.5  550.21  1042.5  553.75  1102.4  561.31  1192.4  585.51  1222.4  592.56
  1252.4  606.06  1302.4  625.71  1372.3  646.55  1412.3  654.34  1462.3  660.27
#Mann= 3 , 0 , 0
       0     .08       0   821.5    .045       0   841.5     .08       0
Bank Sta=821.5,841.5
XS Rating Curve= 0 ,0
Exp/Cntr=0.3,0.1

Type RM Length L Ch R = 1 ,2095.8  ,328.6,320.4,307.2
XS GIS Cut Line= 4
     1516552.514      454132.988     1515961.216      454684.924
     1515902.183      454960.788     1515952.148      455143.993
#Sta/Elev= 30
    10.1  681.01    30.3  680.57    60.7  681.93    80.9  680.87   111.2  673.72
   222.4  642.43   242.7   638.3   333.7  623.65   353.9  618.64   394.3  606.02
   434.8  596.84   475.2  584.99   495.4  581.04   535.9   574.5   566.2   571.3
   616.8  570.27   707.8  561.68   758.3  559.78   778.5   557.9   808.9  553.25
   889.5  547.32   919.7  545.99   970.1  541.93   980.1  541.38   990.1  541.51
  1080.9  551.19    1131   558.2  1200.9  571.37  1250.9  584.04  1280.9  590.94
#Mann= 3 , 0 , 0
       0     .08       0   970.1    .045       0   990.1     .08       0
Bank Sta=970.1,990.1
XS Rating Curve= 0 ,0
Exp/Cntr=0.3,0.1

Type RM Length L Ch R = 1 ,1775.5  ,281.8,288.1,293.4
XS GIS Cut Line= 5
      1516584.25      454056.822     1515840.543      454729.073
     1515687.494      454767.335     1515699.073       455021.72
     1515701.916      455433.221
#Sta/Elev= 30
    10.1  679.32    40.5  678.75      81   668.2    91.1  667.31   141.8  671.31
     162  669.38   232.9  651.05   293.7  633.49   415.2  610.55   425.3  607.77
   465.8  590.05   506.3  579.53   567.1  569.56   648.1  562.82   759.5  556.06
   931.6  547.75  1022.2  544.95  1170.1  544.76  1199.2  539.57  1209.2  539.34
  1219.2  539.68  1307.2  545.62  1385.5  559.65    1425  563.88  1515.3  566.96
  1565.5   571.3  1605.6  570.12  1645.8  570.97  1796.3  578.53  1826.4   581.7
#Mann= 3 , 0 , 0
       0     .08       0  1199.2    .045       0  1219.2     .08       0
Bank Sta=1199.2,1219.2
XS Rating Curve= 0 ,0
Exp/Cntr=0.3,0.1

Type RM Length L Ch R = 1 ,1487.4  ,1504.1,1487.4,1472
XS GIS Cut Line= 4
      1515346.55      453821.977     1515542.237      454542.138
     1515462.392      454875.339      1515213.26      455351.647
#Sta/Elev= 30
    10.1  740.02    80.7  732.18   131.1   728.1   181.5  720.47   201.7  719.65
   312.6  719.47   332.8  717.64   393.3  700.65   463.9  684.56   534.5  669.78
   564.7  662.56     595  654.23   665.6  629.93   746.3  607.29   826.9  580.84
   897.4  552.93   937.8  538.59   947.8  537.28   957.8  537.43  1058.7  545.23
  1139.6  546.53  1159.9  548.77  1200.5  556.55  1251.2   569.6  1393.2  613.76
  1413.5  622.51    1454  643.63  1474.3  651.88  1494.6     659  1626.4  694.86
#Mann= 3 , 0 , 0
       0     .08       0   937.8    .045       0   957.8     .08       0
Bank Sta=937.8,957.8
XS Rating Curve= 0 ,0
Exp/Cntr=0.3,0.1

Chan Stop Cuts=-1
Use User Specified Reach Order=0